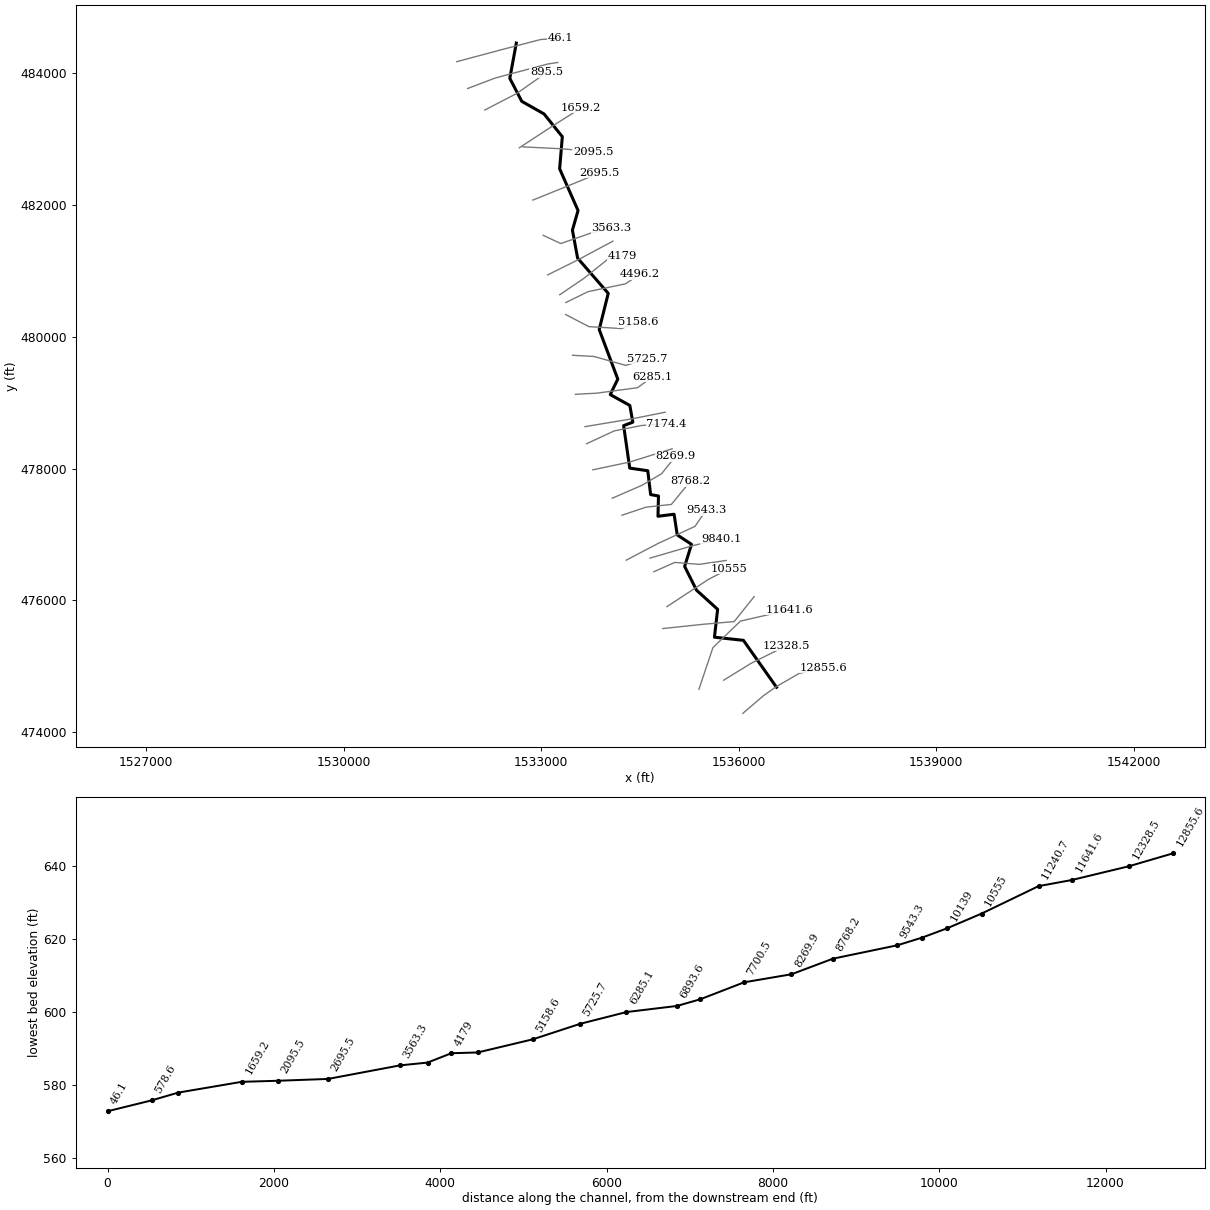
--- BUFFALOCR.prj (project) ---

Proj Title=BUFFALOCR
Current Plan=p01
Default Exp/Contr=0,0
English Units
Geom File=g01
Flow File=f01
Plan File=p01
BEGIN DESCRIPTION:
END DESCRIPTION:
DSS Export Rating Curves= 0
DSS Export Rating Curve Sorted= 0
DSS Export Volume Flow Curves= 0
DXF OffsetX= 0
DXF OffsetY= 0
DXF ScaleX= 0
DXF ScaleY= 0

--- BUFFALOCR.p01 (plan) ---

Plan Title=Floodplain
Program Version=4.00
Geom File=g01
Flow File=f01
K Sum by GR=0
Std Step Tol=0.01
Critical Tol=0.01
Num of Std Step Trials=20
Max Error Tol=0.3
Flow Tol Ratio=0.001
Split Flow NTrial=30
Split Flow Tol=0.02
Split Flow Ratio=0.02
Log Output Level=0
Friction Slope Method=1
Unsteady Friction Slope Method=2
Unsteady Bridges Friction Slope Method=1
Global Log Level=0
CheckData=False
Run HTab=0
Run UNet=0
Run PostProcess=0
UNET Theta=0
UNET Theta Warmup=0
UNET ZTol=0
UNET ZSATol=0
UNET MxIter=0
UNET MaxInSteps=0
UNET DtIC=0
UNET DtMin=0
UNET MaxCRTS=0
UNET WFStab=0
UNET SFStab=0
UNET WFX=0
UNET SFX=0
UNET DSS MLevel=0
UNET DZMax Abort=0
UNET Convert EG Bridges=0
UNET Use Existing IB Tables=0
UNET Froude Limit=0
UNET Froude Power=0
Write IC File=0
Echo Input=False
Echo Output=False
Write Detailed=0

--- BUFFALOCR.f01 (steady flow) ---

Flow Title=NFF Regression Equation
Program Version=4.00
Number of Profiles=1
Profile Names=P100yr
River Rch & RM=BUFFALOCR,Main      ,12855.6
     371
River Rch & RM=BUFFALOCR,Main      ,11641.6
     392
River Rch & RM=BUFFALOCR,Main      ,11240.7
     469
River Rch & RM=BUFFALOCR,Main      ,10139
     519
River Rch & RM=BUFFALOCR,Main      ,7174.4
     573
River Rch & RM=BUFFALOCR,Main      ,6893.6
     631
River Rch & RM=BUFFALOCR,Main      ,4496.2
     679
River Rch & RM=BUFFALOCR,Main      ,4179
     767
River Rch & RM=BUFFALOCR,Main      ,3893.6
     812
River Rch & RM=BUFFALOCR,Main      ,2695.5
     866
River Rch & RM=BUFFALOCR,Main      ,895.5
     919
Boundary for River Rch & Prof#=BUFFALOCR,Main      ,1
Up Type=0
Dn Type=3
Dn Slope=0.005399

--- BUFFALOCR.g01 (geometry) ---

Geom Title=USGS 10m DEM
Program Version=4.00

River Reach=BUFFALOCR       ,Main
Reach XY= 30
     1536573.804      474683.171      1536071.16      475395.291
     1535631.062      475442.947     1535679.417      475866.102
     1535358.935      476156.137     1535178.421      476516.976
     1535282.811      476852.184     1535065.791        476995.4
     1535018.312      477308.771     1534773.822      477278.044
     1534781.114      477585.672     1534662.001       477607.03
     1534618.537      477968.508     1534344.632      478009.123
     1534252.051      478653.351     1534391.945      478705.894
     1534345.768      478959.779     1534048.357      479124.598
     1534163.415       479359.12     1533881.051      480111.587
     1534018.083      480660.606     1533553.129      481195.229
     1533474.223      481620.663      1533559.72      481917.588
     1533280.101       482550.95     1533320.928      483038.045
     1533043.506      483383.393     1532705.168       483574.42
     1532523.302      483923.703     1532622.131      484458.169

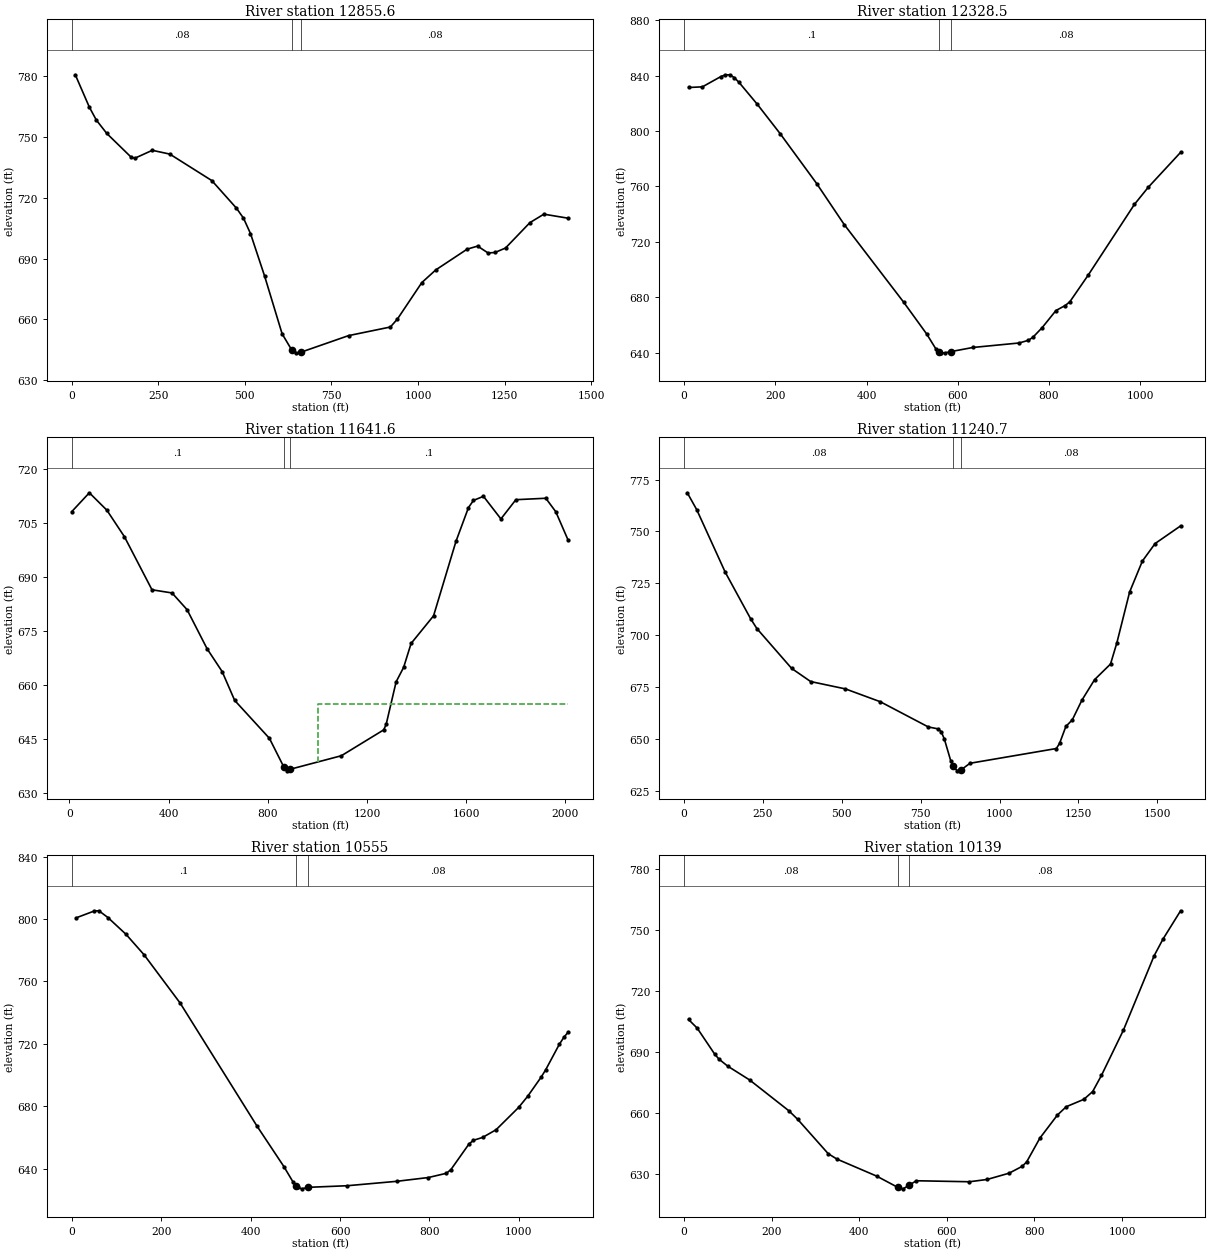
Type RM Length L Ch R = 1 ,12855.6 ,530.7,527,525.9
XS GIS Cut Line= 5
     1536062.686       474286.93     1536369.449       474550.55
     1536568.281      474691.508      1536917.31      474893.309
     1537290.751      474977.717
#Sta/Elev= 30
    10.1  780.71    50.6  764.77    70.8  758.38   101.1  751.76   171.9  739.98
     182  739.54   232.6  743.45   283.1  741.58   404.5  728.51   475.6  714.91
   495.9     710   516.2  702.39   556.8   681.5   607.6  652.91   635.7  644.83
   648.2  643.54   660.7  643.78   799.4  652.03   920.3  656.28   940.5  660.18
  1011.1  678.19  1051.4  684.44    1142  694.68  1172.3   696.2  1202.5   692.8
  1222.7  693.05  1252.9  695.25  1323.4  707.77  1363.7  711.95  1434.2  709.94
#Mann= 3 , 0 , 0
       0     .08       0   635.7    .045       0   660.7     .08       0
Bank Sta=635.7,660.7
XS Rating Curve= 0 ,0
Exp/Cntr=0.3,0.1

Type RM Length L Ch R = 1 ,12328.5 ,703.3,686.9,683.7
XS GIS Cut Line= 3
     1535770.804      474790.319     1536180.769      475042.662
     1536723.952      475314.253
#Sta/Elev= 30
      10  831.36    40.1  831.83    80.2  839.18    90.3  840.45   100.3  840.53
   110.3  838.39   120.4  835.05   160.5  819.25   210.6  798.07   290.8  762.04
     351  732.56   481.4  676.55     532  653.57   552.3  642.72     560  640.67
   562.4  640.03   572.5  640.02     585  640.91   633.2  643.89   734.4  647.12
   754.7  649.02   764.8  651.22   785.1  658.18   815.4  670.54   835.7  674.14
   845.8  676.82   886.3  696.17   987.5  747.08  1017.8  759.41  1088.7  784.57
#Mann= 3 , 0 , 0
       0      .1       0     560    .045       0     585     .08       0
Bank Sta=560,585
XS Rating Curve= 0 ,0
Exp/Cntr=0.3,0.1

Type RM Length L Ch R = 1 ,11641.6 ,394.8,401,393.7
XS GIS Cut Line= 4
     1535395.516      474652.988     1535608.066      475284.733
     1536026.075      475687.385     1536771.185      475857.436
#Sta/Elev= 30
    10.1  708.24    80.8  713.46   151.5  708.62   222.2  701.26   333.3  686.52
   414.1  685.64   474.7     681   555.5  670.13     616  663.82   666.5  655.81
   806.6  645.27   864.2  637.37   876.7  636.24   889.2  636.66  1096.8  640.44
  1267.1  647.61  1277.1  649.11  1317.3  660.96  1347.5  664.96  1377.7  671.62
  1468.2  679.29  1558.7     700    1609  709.36  1629.1  711.34  1669.3  712.48
  1739.7   706.2    1800  711.54  1920.7  711.94  1960.9  708.19  2011.2  700.21
#Mann= 3 , 0 , 0
    10.1      .1       0   864.2    .045       0   889.2      .1       0
#XS Ineff= 2 , 0
                         1003.57           654.8
Permanent Ineff=
       F       F
Bank Sta=864.2,889.2
XS Rating Curve= 0 ,0
Exp/Cntr=0.3,0.1

Type RM Length L Ch R = 1 ,11240.7 ,672.6,685.6,698.9
XS GIS Cut Line= 4
      1534846.43      475574.036     1535454.905      475638.383
     1535930.664      475679.954     1536233.907      476058.177
#Sta/Elev= 30
      10  768.62    40.1  760.43   130.4  730.31   210.6  707.96   230.7  703.15
     341  683.93   401.2   677.6   511.6  674.05     622  667.87   774.4   655.7
   804.9   654.8   815.1  653.44   825.3   649.8   845.6  639.28   853.4  636.69
   865.9  634.55   878.4  635.06   906.5   638.2  1180.3  645.31  1190.4  647.77
  1210.6     656  1230.8  659.12  1261.1  668.57  1301.5  678.52    1352  686.04
  1372.2   696.3  1412.6  720.78    1453  735.69  1493.4  744.15  1574.2  752.65
#Mann= 3 , 0 , 0
       0     .08       0   853.4    .045       0   878.4     .08       0
Bank Sta=853.4,878.4
XS Rating Curve= 0 ,0
Exp/Cntr=0.3,0.1

Type RM Length L Ch R = 1 ,10555   ,434.4,416.1,397.8
XS GIS Cut Line= 3
     1534909.862      475906.286     1535542.667      476321.997
     1535856.759      476483.662
#Sta/Elev= 30
    10.1  800.86    50.5  805.24    60.6  805.35    80.8  801.01   121.1   790.3
   161.5  777.18   242.3  746.16   413.9  667.39   474.5  641.21   494.7  631.45
   502.4  628.72   504.8  627.87   514.9     627   527.4  627.96   615.8  628.99
   726.9  631.83   797.5  634.26   837.9  636.98     848  639.38   888.3  655.76
   898.4  658.15   918.6  659.95   948.9  664.89   999.4  679.22  1019.6  686.35
  1049.8  698.68  1059.9  703.37  1090.2  719.61  1100.3  724.08  1110.4  727.61
#Mann= 3 , 0 , 0
       0      .1       0   502.4    .045       0   527.4     .08       0
Bank Sta=502.4,527.4
XS Rating Curve= 0 ,0
Exp/Cntr=0.3,0.1

Type RM Length L Ch R = 1 ,10139   ,288.4,298.8,308.1
XS GIS Cut Line= 4
     1534710.634      476436.043     1535029.459      476577.743
      1535401.42      476548.222     1535808.807      476607.264
#Sta/Elev= 30
      10  706.12    29.9  701.86    69.8   689.1    79.7  686.62    99.7  683.18
   149.5  676.43   239.2  661.28   259.2  657.11     329  640.22   348.9  637.57
   439.7   629.2   487.7   623.7   500.2  622.95   512.7  624.63   530.4  626.92
   651.4  626.43   691.8  627.55   742.1  630.64   772.2  634.03   782.3  636.22
   812.4  647.86   852.5  659.21   872.6  663.28   912.8   666.9   932.9  670.72
   952.9  678.62  1003.1  700.87  1073.4  737.47  1093.5  745.59  1133.7   759.5
#Mann= 3 , 0 , 0
       0     .08       0   487.7    .045       0   512.7     .08       0
Bank Sta=487.7,512.7
XS Rating Curve= 0 ,0
Exp/Cntr=0.3,0.1

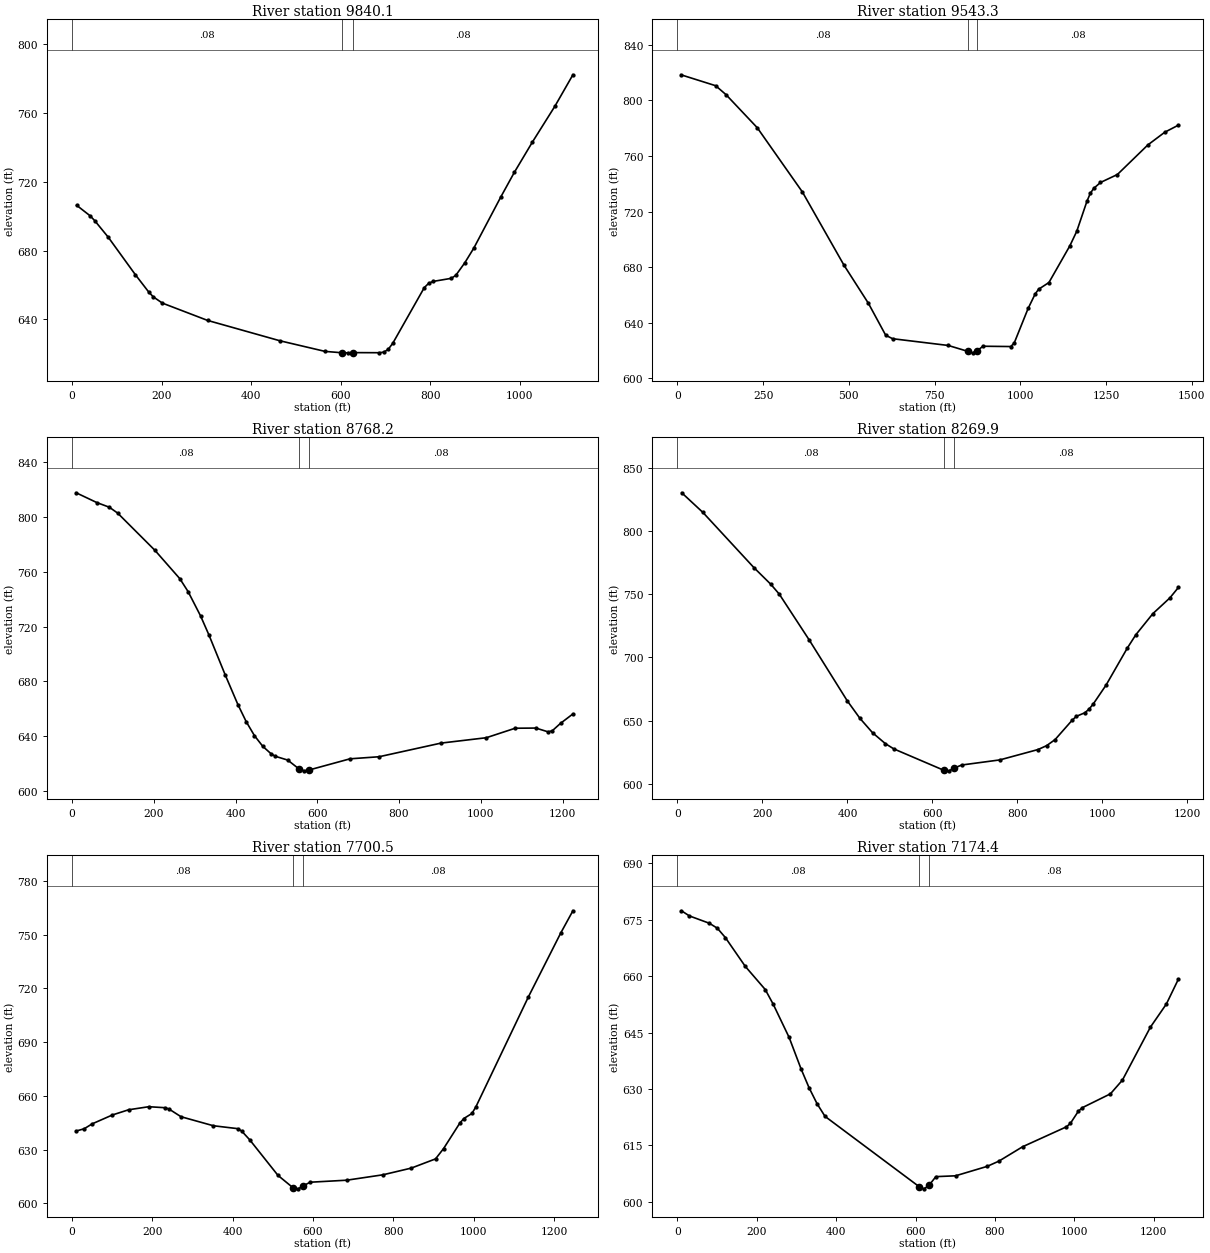
Type RM Length L Ch R = 1 ,9840.1  ,291.9,296.8,302.9
XS GIS Cut Line= 3
     1534651.839      476642.982      1535301.05      476831.622
     1535732.053      476931.993
#Sta/Elev= 30
    10.1  706.37    40.4  700.21    50.5  697.44    80.7  687.81   141.3  665.97
   171.5  655.75   181.6  652.99   201.8  649.37   302.7  639.29   464.2  627.44
   565.1  621.25     603  620.45   615.5  620.41     628  620.54   686.1  620.48
   696.2  620.81   706.2  622.46   716.3  625.97   786.7  658.39   796.8  660.97
   806.8  662.02     847   663.8   857.1  665.55   877.2  672.86   897.3  681.39
   957.7  711.24   987.8  725.51  1028.1  743.13  1078.4  764.02  1118.6  782.33
#Mann= 3 , 0 , 0
       0     .08       0     603    .045       0     628     .08       0
Bank Sta=603,628
XS Rating Curve= 0 ,0
Exp/Cntr=0.3,0.1

Type RM Length L Ch R = 1 ,9543.3  ,780.5,775.1,768
XS GIS Cut Line= 4
     1534291.439      476611.678      1534775.58      476865.557
     1535336.475       477125.34      1535503.78      477370.073
#Sta/Elev= 30
    10.1  818.39   111.4  810.52   141.7  804.06   232.8  780.27   364.4  734.06
   485.9  681.31   556.8  654.03   607.5  630.95   627.7  628.47   789.9  623.62
   848.3  619.29   860.8  618.31   873.3  619.61   891.2  623.06   972.3  622.84
   982.4  625.39  1022.9  650.23  1043.2  660.52  1053.3  664.03  1083.7  668.92
  1144.5  695.22  1164.8  705.76  1194.4  727.27  1204.3  733.06  1214.2  736.61
    1234  740.88  1283.4  746.63  1372.3  767.92  1421.7  777.07  1461.3  782.13
#Mann= 3 , 0 , 0
       0     .08       0   848.3    .045       0   873.3     .08       0
Bank Sta=848.3,873.3
XS Rating Curve= 0 ,0
Exp/Cntr=0.3,0.1

Type RM Length L Ch R = 1 ,8768.2  ,484.7,498.3,510.5
XS GIS Cut Line= 4
     1534226.845      477294.227     1534592.551      477416.133
     1534976.321      477457.463     1535264.935      477807.758
#Sta/Elev= 30
    10.1  817.68    60.9   810.5    91.3  807.13   111.6  802.85   202.9  775.63
   263.8  754.92     284  745.51   314.5  727.76   334.8  713.96   375.3  684.31
   405.8  663.04   426.1  650.57   446.4  640.28   466.8  632.49   487.1  627.06
   497.2  625.27   527.7  622.49   555.8   615.9   568.3  614.63   580.8  615.32
   680.1  623.41   751.2  624.92   902.6  634.88  1013.5  638.81  1084.1  645.74
  1134.6  645.87  1164.8   643.1  1174.9  643.88  1195.1  649.31  1225.4  656.18
#Mann= 3 , 0 , 0
       0     .08       0   555.8    .045       0   580.8     .08       0
Bank Sta=555.8,580.8
XS Rating Curve= 0 ,0
Exp/Cntr=0.3,0.1

Type RM Length L Ch R = 1 ,8269.9  ,576.1,569.4,562.8
XS GIS Cut Line= 4
     1534078.889      477551.929     1534527.605      477746.766
     1534828.717      477923.891     1535041.267      478189.578
#Sta/Elev= 30
      10  830.22    59.9  814.65   179.7   771.1   219.6  757.87   239.6  750.05
   309.5   714.1   399.3  665.84   429.3  651.89   459.2  640.43   489.2  631.87
   509.2  627.69   626.4  610.85   638.9  610.35   651.4  612.56   668.9  614.96
   758.7     619   848.5  627.19   868.6  630.24   888.6  635.03   928.6  650.29
   938.6  653.42   958.6  656.26   968.6  659.15   978.6  663.27  1008.7  678.19
  1058.7  707.46  1078.7  717.96  1118.7  734.63  1158.8  747.09  1178.8  755.33
#Mann= 3 , 0 , 0
       0     .08       0   626.4    .045       0   651.4     .08       0
Bank Sta=626.4,651.4
XS Rating Curve= 0 ,0
Exp/Cntr=0.3,0.1

Type RM Length L Ch R = 1 ,7700.5  ,525.8,526.1,524.8
XS GIS Cut Line= 3
     1533783.681      477982.933     1534344.576      478101.016
      1534988.13      478301.757
#Sta/Elev= 30
    10.1  640.39    30.2  641.66    50.3  644.42   100.6  649.37   140.8  652.26
   191.1  653.97   231.3  653.42   241.3   652.7   271.5  648.38     352  643.35
   412.3  641.74   422.4   640.4   442.5   635.5   512.9  615.64   550.6   608.7
   563.1  608.14   575.6  609.84   593.3  611.84   683.9  612.96   774.4  615.98
   844.9  619.72   905.2  624.85   925.3  630.62   965.6  644.79   975.7  647.39
   995.8  650.19  1005.8  653.94  1136.6  715.33  1217.1  750.95  1247.3  763.32
#Mann= 3 , 0 , 0
       0     .08       0   550.6    .045       0   575.6     .08       0
Bank Sta=550.6,575.6
XS Rating Curve= 0 ,0
Exp/Cntr=0.3,0.1

Type RM Length L Ch R = 1 ,7174.4  ,281.6,280.8,271
XS GIS Cut Line= 4
     1533689.215      478378.511      1534108.41      478573.348
     1534527.605      478656.006     1534899.567      478679.623
#Sta/Elev= 30
      10  677.33    30.1  675.96    80.4  674.01   100.5  672.69   120.6  670.22
   170.8  662.57   221.1  656.42   241.2  652.52   281.4  643.68   311.5  635.31
   331.6  630.33   351.7   626.1   371.8  622.73   608.7  604.09   621.2  603.49
   633.7  604.41   651.1  606.73   700.7  606.95   780.2  609.45     810  610.85
   869.7  614.67   980.2  619.96   990.3   620.9  1010.4  624.14  1020.5  625.06
    1091  628.72  1121.2  632.36  1191.7  646.42    1232  652.58  1262.2  659.16
#Mann= 3 , 0 , 0
       0     .08       0   608.7    .045       0   633.7     .08       0
Bank Sta=608.7,633.7
XS Rating Curve= 0 ,0
Exp/Cntr=0.3,0.1

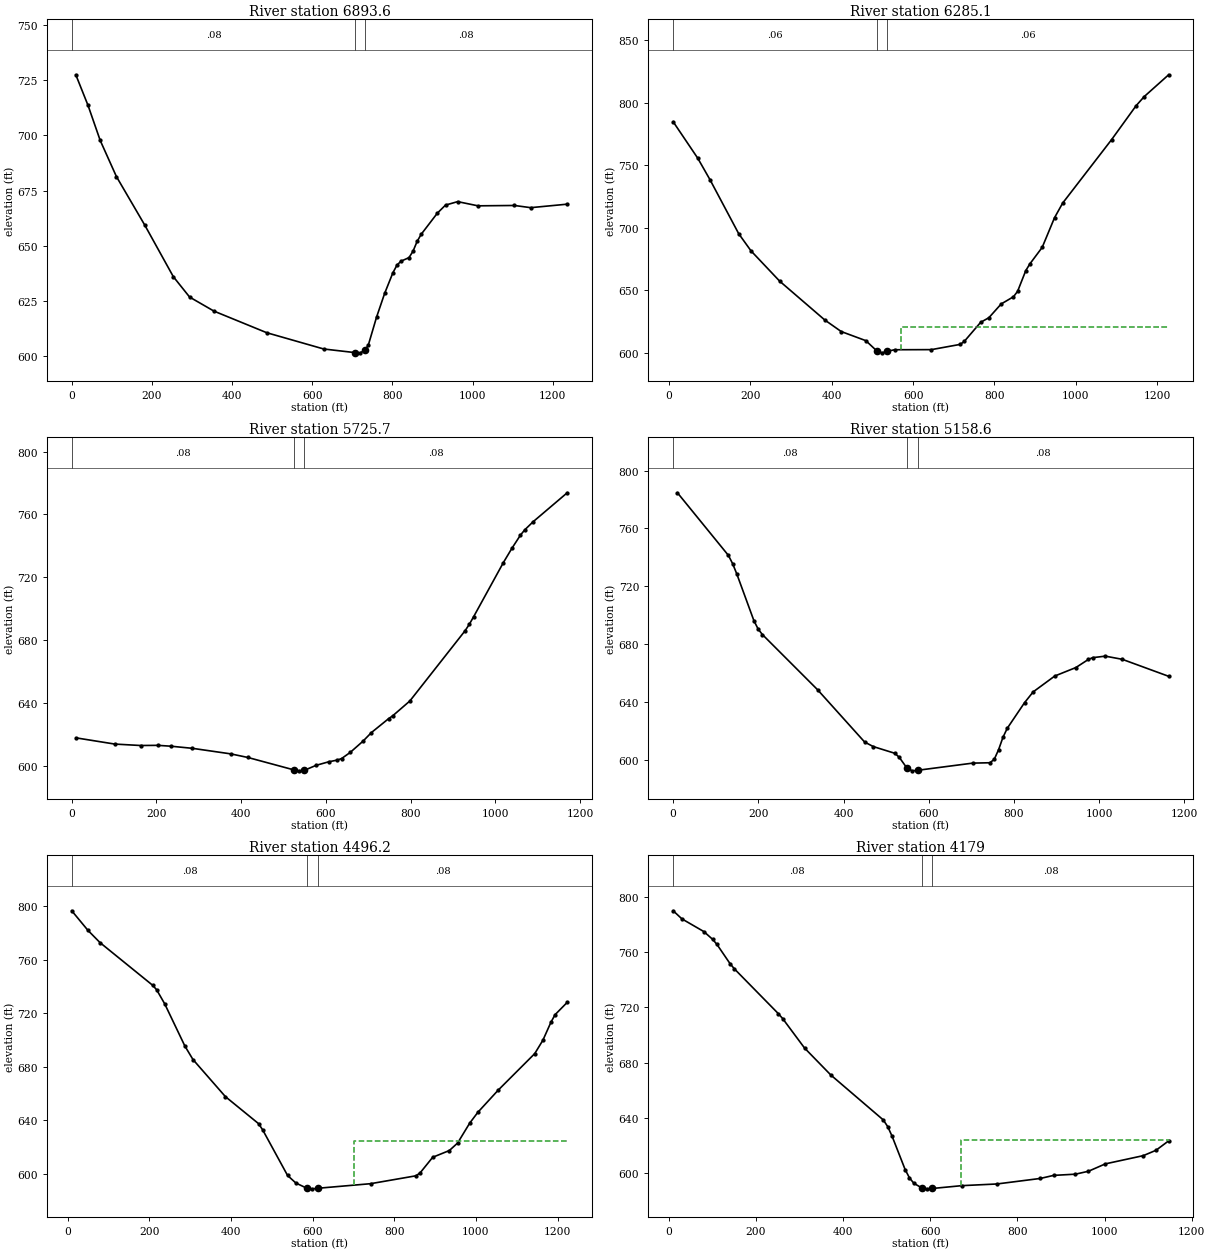
Type RM Length L Ch R = 1 ,6893.6  ,609.3,608.4,606.6
XS GIS Cut Line= 3
     1533665.598      478638.294     1534385.679      478757.724
     1534881.855      478856.748
#Sta/Elev= 30
    10.1  727.45    40.6   713.6      71  697.73   111.5  681.37   182.5  659.32
   253.4   636.1     294  626.88   354.8  620.52   486.6  610.74   628.5  603.39
   707.3  601.74   719.8  601.65   732.3  602.99     740   605.3   760.3  617.79
   780.5  628.55   800.8  637.76   810.9  641.23     821   643.1   841.2  644.72
   851.3  647.64   861.5  652.06   871.6  655.27   912.1  664.87   932.3  668.49
   962.7  670.06  1013.3  668.16  1104.3  668.32  1144.8  667.33  1235.9  668.91
#Mann= 3 , 0 , 0
       0     .08       0   707.3    .045       0   732.3     .08       0
Bank Sta=707.3,732.3
XS Rating Curve= 0 ,0
Exp/Cntr=0.3,0.1

Type RM Length L Ch R = 1 ,6285.1  ,570.4,559.4,548.4
XS GIS Cut Line= 4
     1533520.781      479129.137     1533842.723      479146.052
      1534462.66       479228.71     1534689.643      479393.686
#Sta/Elev= 30
    10.1   784.7    70.5  755.59   100.7  738.35   171.3  695.18   201.5  681.49
     272  657.27   382.9  626.23   423.3     617   483.8  609.71   511.6  601.28
   524.1  599.97   536.6   601.2   554.4  602.44   645.2  602.54   715.8  606.72
   725.9   609.1   766.2  624.37   786.4  628.04   816.7  639.05   846.9  644.81
     857  649.12   877.2  665.75   887.3  671.11   917.5  684.27   947.8  707.96
   967.9   719.7  1088.1  770.38  1148.2  797.43  1168.3  804.79  1228.4  822.25
#Mann= 3 , 0 , 0
    10.1     .06       0   511.6    .045       0   536.6     .06       0
#XS Ineff= 2 , 0
                          571.33          620.41
Permanent Ineff=
       F       F
Bank Sta=511.6,536.6
XS Rating Curve= 0 ,0
Exp/Cntr=0.3,0.1

Type RM Length L Ch R = 1 ,5725.7  ,561.4,567.1,572.9
XS GIS Cut Line= 4
      1533475.38      479721.083     1533800.109      479703.371
      1534284.25      479567.575     1534610.674      479667.455
#Sta/Elev= 30
    10.2  617.71   101.6  613.76   162.6  612.85   203.3  612.95   233.7  612.41
   284.6  611.06   375.5  607.51   415.7  605.23   523.9  597.35   536.4  596.72
   548.9  597.04   576.6  600.21   606.8   602.5   626.9  603.57     637  604.57
   657.1  608.41   687.2  615.55   707.4  621.11   747.6  629.89   757.6  631.77
   797.9  641.17   928.4  685.93   938.5  690.09   948.5  694.83  1018.8  729.35
  1038.9  738.42    1059  746.77    1069  750.11  1089.1  755.35  1169.4  773.75
#Mann= 3 , 0 , 0
       0     .08       0   523.9    .045       0   548.9     .08       0
Bank Sta=523.9,548.9
XS Rating Curve= 0 ,0
Exp/Cntr=0.3,0.1

Type RM Length L Ch R = 1 ,5158.6  ,657.2,662.4,669.9
XS GIS Cut Line= 4
     1533370.831       480339.57      1533724.64      480155.663
     1534220.589      480126.142     1534469.968      480222.088
#Sta/Elev= 30
      10  784.62   129.6  741.37   139.6  735.61   149.5  728.41   189.4  696.31
   199.4  690.46   209.3  686.69   338.9  648.53   449.4  612.37   469.7  609.24
   520.4  604.59   530.6  601.82   548.5  594.46     561  592.48   573.5  592.85
   702.9  597.81   743.5  598.07   753.6  600.46   763.8  607.15   773.9  615.56
     784  621.85   824.6  639.56   844.9  647.04   895.6     658   945.1  663.85
   974.7   669.5   984.6  670.69  1014.3  671.73  1053.9  669.55  1162.8  657.81
#Mann= 3 , 0 , 0
       0     .08       0   548.5    .045       0   573.5     .08       0
Bank Sta=548.5,573.5
XS Rating Curve= 0 ,0
Exp/Cntr=0.3,0.1

Type RM Length L Ch R = 1 ,4496.2  ,302.1,317.2,329.2
XS GIS Cut Line= 4
     1533375.013      480521.698     1533712.831      480687.037
     1534279.631       480805.12     1534503.989      480952.724
#Sta/Elev= 30
     9.9  796.53    49.5  781.93    79.2  772.74   207.8  740.96   217.7  737.61
   237.5  727.09     287  695.52   306.8  685.46   386.3  657.73   467.5  637.56
   477.7  632.85   538.6  598.85   558.9  593.21   587.1  589.15   599.6  588.87
   612.1  589.28   741.8  592.71   853.5  598.63   863.7  600.96   894.1  612.45
   934.8  617.46   955.1  623.08   984.9  638.01  1004.8  646.06  1054.5  662.57
  1144.1  689.88    1164  699.85  1183.8  713.32  1193.8  718.91  1223.6  728.13
#Mann= 3 , 0 , 0
     9.9     .08       0   587.1    .045       0   612.1     .08       0
#XS Ineff= 2 , 0
                          701.63          624.35
Permanent Ineff=
       F       F
Bank Sta=587.1,612.1
XS Rating Curve= 0 ,0
Exp/Cntr=0.3,0.1

Type RM Length L Ch R = 1 ,4179    ,291.9,285.4,279.8
XS GIS Cut Line= 4
     1533281.828      480639.803     1533647.886      480887.778
     1534055.273      481212.507     1534238.301      481230.219
#Sta/Elev= 30
      10  789.76    30.1   783.9    80.4  774.72   100.5  769.13   110.5  765.42
   140.7  751.44   150.7  747.68   251.2  715.41   261.3  711.79   311.5  690.49
   371.8  670.98   492.2  638.49   502.3  633.69   512.3  626.78   542.3  602.63
   552.3  596.58   562.4  592.66   579.9  589.45   592.4  588.66   604.9  588.92
   672.6  590.97   752.7  592.17   852.9  596.19     883  598.39   933.1  599.26
   963.1  601.39  1001.8  606.72  1088.9  612.67    1118  616.54    1147  623.35
#Mann= 3 , 0 , 0
      10     .08       0   579.9    .045       0   604.9     .08       0
#XS Ineff= 2 , 0
                          669.79          624.24
Permanent Ineff=
       F       F
Bank Sta=579.9,604.9
XS Rating Curve= 0 ,0
Exp/Cntr=0.3,0.1

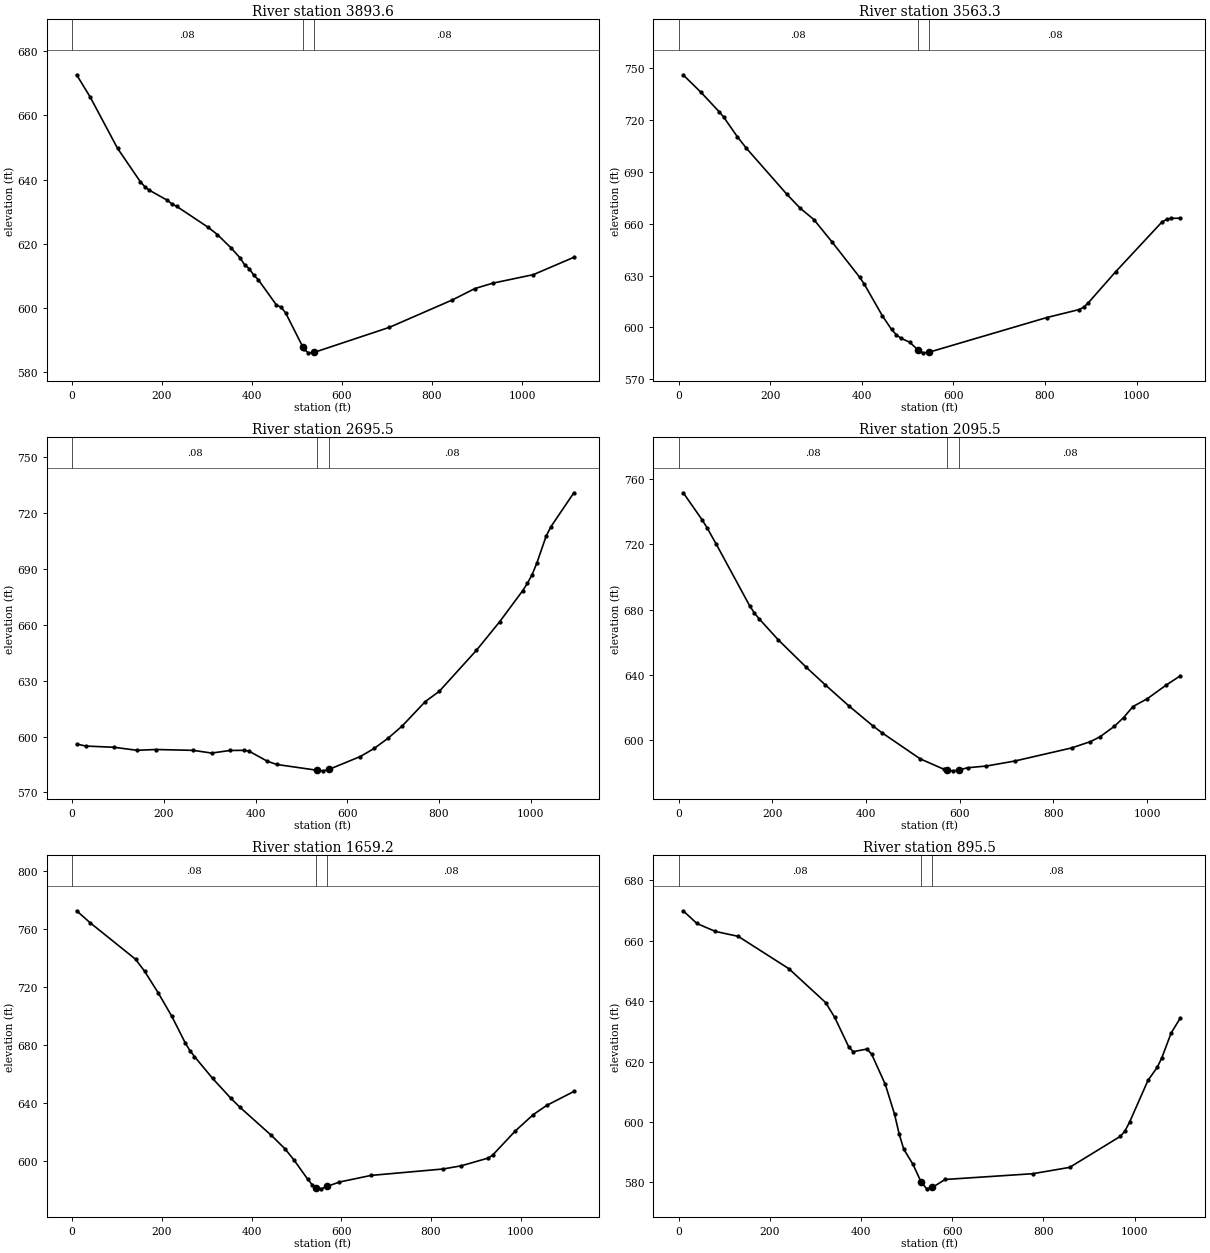
Type RM Length L Ch R = 1 ,3893.6  ,333.9,330.3,325.9
XS GIS Cut Line= 3
     1533098.799      480940.915     1533568.939      481174.473
     1534089.328      481453.034
#Sta/Elev= 30
    10.1  672.68    40.4  665.71     101  649.79   151.4  639.44   161.5  637.86
   171.6  636.74     212  633.58   222.1  632.44   232.2  631.73   302.9  625.14
   323.1  622.91   353.3  618.77   373.5  615.63   383.6  613.48   393.7  612.31
   403.8  610.28   413.9  608.86   454.3  600.97   464.4  600.31   474.5  598.57
   512.5  588.02   514.9  587.37     525  586.09   537.5  586.21     705  594.02
   845.1  602.56   895.1   606.1   935.1  607.79  1025.2  610.44  1115.2  615.84
#Mann= 3 , 0 , 0
       0     .08       0   512.5    .045       0   537.5     .08       0
Bank Sta=512.5,537.5
XS Rating Curve= 0 ,0
Exp/Cntr=0.3,0.1

Type RM Length L Ch R = 1 ,3563.3  ,866.3,867.7,869.3
XS GIS Cut Line= 4
     1533029.925      481541.478     1533297.828      481416.764
     1533778.205      481583.049     1534062.727      481646.326
#Sta/Elev= 30
     9.9     746    49.3  735.79    88.7  724.63    98.5  721.57   128.1  710.29
   147.8  703.64   236.4  676.97     266  668.79   295.5  662.32   335.4   649.3
   395.2  629.06   405.2  625.12     445  606.69     465  598.82   474.9  595.92
   484.9  593.84   504.8  591.45   522.2  587.08   524.8  586.42   534.7  585.33
   547.2  585.73   803.9  605.73   874.2  610.32   884.3  611.68   894.3  614.21
   954.6  632.32  1055.1   660.9  1065.2  662.41  1075.2  663.06  1095.3  663.11
#Mann= 3 , 0 , 0
       0     .08       0   522.2    .045       0   547.2     .08       0
Bank Sta=522.2,547.2
XS Rating Curve= 0 ,0
Exp/Cntr=0.3,0.1

Type RM Length L Ch R = 1 ,2695.5  ,611.7,600,586.9
XS GIS Cut Line= 3
     1532873.596      482076.309     1533381.444      482280.996
     1533886.899      482488.683
#Sta/Elev= 30
    10.1  595.96    30.4   594.9    91.3  594.24     142  592.62   182.5  593.05
   263.6   592.6   304.2  591.15   344.8  592.54   375.2   592.6   385.3  592.23
   425.9  586.74   446.1  585.02     535  581.89   547.5   581.6     560  582.36
   628.5  589.29   658.9  593.66   689.2  599.15   719.6  605.64   770.2   618.8
   800.5  624.26   881.5  646.27   932.1  661.58   982.7  678.39   992.8  682.29
  1002.9  686.88    1013   692.9  1033.3  707.38  1043.4  712.42    1094  730.84
#Mann= 3 , 0 , 0
       0     .08       0     535    .045       0     560     .08       0
Bank Sta=535,560
XS Rating Curve= 0 ,0
Exp/Cntr=0.3,0.1

Type RM Length L Ch R = 1 ,2095.5  ,418.9,436.3,454.9
XS GIS Cut Line= 3
     1532720.933      482883.383     1533306.875      482854.934
     1533789.585      482812.533
#Sta/Elev= 30
    10.1  751.64    50.6  734.94    60.7  730.28    80.9  719.94   151.7  682.41
   161.8  677.95   171.9   674.4   212.4  661.59   273.1  644.49   313.5  633.78
   364.1  620.82   414.7  608.71   434.9  604.34   515.8  588.47   566.4  582.07
   574.1  581.41   586.6   581.1   599.1  581.59   616.9     583   657.3  584.05
   717.9  587.12     839  595.14   879.4  599.02   899.6  601.96   929.9   608.3
   950.1  613.78   970.2  620.56  1000.5  625.29  1040.9  633.67  1071.2  639.38
#Mann= 3 , 0 , 0
       0     .08       0   574.1    .045       0   599.1     .08       0
Bank Sta=574.1,599.1
XS Rating Curve= 0 ,0
Exp/Cntr=0.3,0.1

Type RM Length L Ch R = 1 ,1659.2  ,766.7,763.7,764.5
XS GIS Cut Line= 3
     1532667.742      482869.443     1533157.841      483190.399
     1533607.423      483475.778
#Sta/Elev= 30
    10.1  772.67    40.4  764.37   141.4  739.25   161.6  730.97   191.9  716.07
   222.2  699.91   252.5  681.35   262.6  676.22   272.7  672.11   313.1  657.07
   353.5  643.41   373.7  637.21   444.4  617.62   474.7  608.37   494.9  600.58
   525.2  587.42   535.3  583.57     543  581.71   555.5  580.81     568  582.47
   595.9  585.51   666.2  590.07     827  594.51   867.2   596.7   927.4  602.04
   937.5  604.15   987.7  620.71  1027.9  632.05  1058.1  638.43  1118.3  647.98
#Mann= 3 , 0 , 0
       0     .08       0     543    .045       0     568     .08       0
Bank Sta=543,568
XS Rating Curve= 0 ,0
Exp/Cntr=0.3,0.1

Type RM Length L Ch R = 1 ,895.5   ,322.3,317,307.9
XS GIS Cut Line= 3
     1532142.715      483442.644     1532626.417      483692.009
     1533081.224      484012.205
#Sta/Elev= 30
    10.1  669.95    40.3  665.74    80.6  663.12     131  661.47   241.9  650.77
   322.5  639.56   342.6  634.61   372.9  624.98     383  623.29   413.2  624.15
   423.3  622.51   453.5  612.42   473.7  602.56   483.7  596.08   493.8     591
     514  585.99   531.7  580.21   544.2  577.85   556.7  578.33   584.6  580.95
   776.8  582.86   857.7  584.96   968.9  595.24   979.1  597.03   989.2  599.97
  1029.6  613.82  1049.8  618.09    1060  621.31  1080.2  629.44  1100.4  634.43
#Mann= 3 , 0 , 0
       0     .08       0   531.7    .045       0   556.7     .08       0
Bank Sta=531.7,556.7
XS Rating Curve= 0 ,0
Exp/Cntr=0.3,0.1

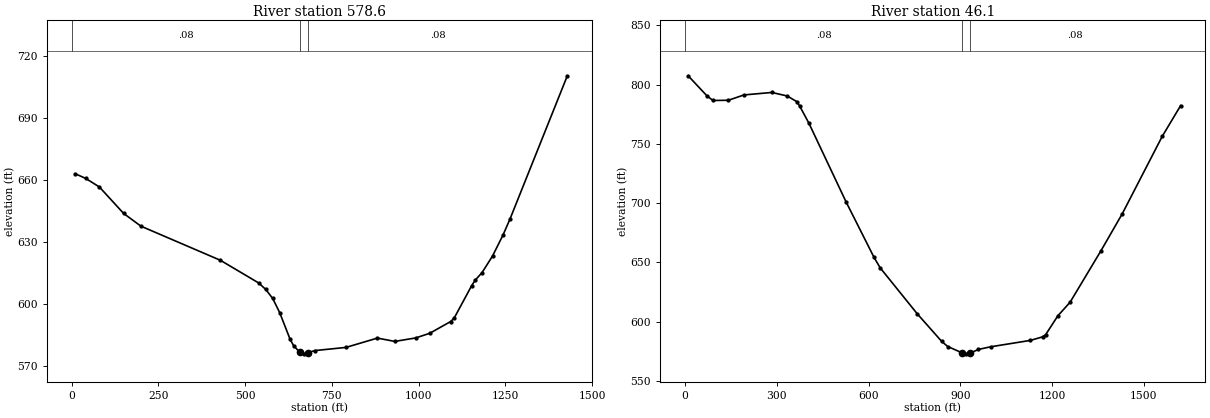
Type RM Length L Ch R = 1 ,578.6   ,529.9,532.5,548.5
XS GIS Cut Line= 4
     1531882.543      483769.007     1532301.738      483928.419
     1533098.799      484140.969     1533252.307      484164.585
#Sta/Elev= 30
      10  662.95    39.9  660.74    79.7  656.55   149.5  643.75   199.3  637.58
   428.6  621.04     539  610.05   559.1  606.96   579.3  602.56   599.4  595.72
   629.6  582.73   639.6   579.7   657.3  576.49   669.8  575.73   682.3  576.33
     700   577.3   790.5  578.84   881.1  583.36   931.4  581.75   991.7  583.44
    1032  585.68  1092.3  591.37  1102.4  593.02  1152.7  608.69  1162.7  611.32
  1182.9  615.09    1213  623.08  1243.2  633.24  1263.3  640.97  1428.7  710.42
#Mann= 3 , 0 , 0
       0     .08       0   657.3    .045       0   682.3     .08       0
Bank Sta=657.3,682.3
XS Rating Curve= 0 ,0
Exp/Cntr=0.3,0.1

Type RM Length L Ch R = 1 ,46.1    ,62.2,46.1,29.9
XS GIS Cut Line= 4
     1531717.226      484176.394     1532402.109      484359.423
     1532992.524      484512.931     1533293.636      484530.643
#Sta/Elev= 30
    10.1  807.48    70.9  790.72    91.1  786.61   141.8  786.82   192.4   791.3
   283.6   793.4   334.2  790.41   364.6  785.75   374.7  781.99   405.1  767.35
   526.6  700.96   617.8  654.24     638  645.35   758.9  606.64   838.9  583.31
   858.9  578.92   906.4  573.51   918.9  572.73   931.4  573.22   958.9  576.41
   998.9  578.67  1128.9  584.06    1169  587.05    1179  588.85    1219  604.81
    1259  616.27  1359.2  659.39  1429.6  690.93  1560.3   756.3  1620.6  782.31
#Mann= 3 , 0 , 0
       0     .08       0   906.4    .045       0   931.4     .08       0
Bank Sta=906.4,931.4
XS Rating Curve= 0 ,0
Exp/Cntr=0.3,0.1

Chan Stop Cuts=-1
Use User Specified Reach Order=0